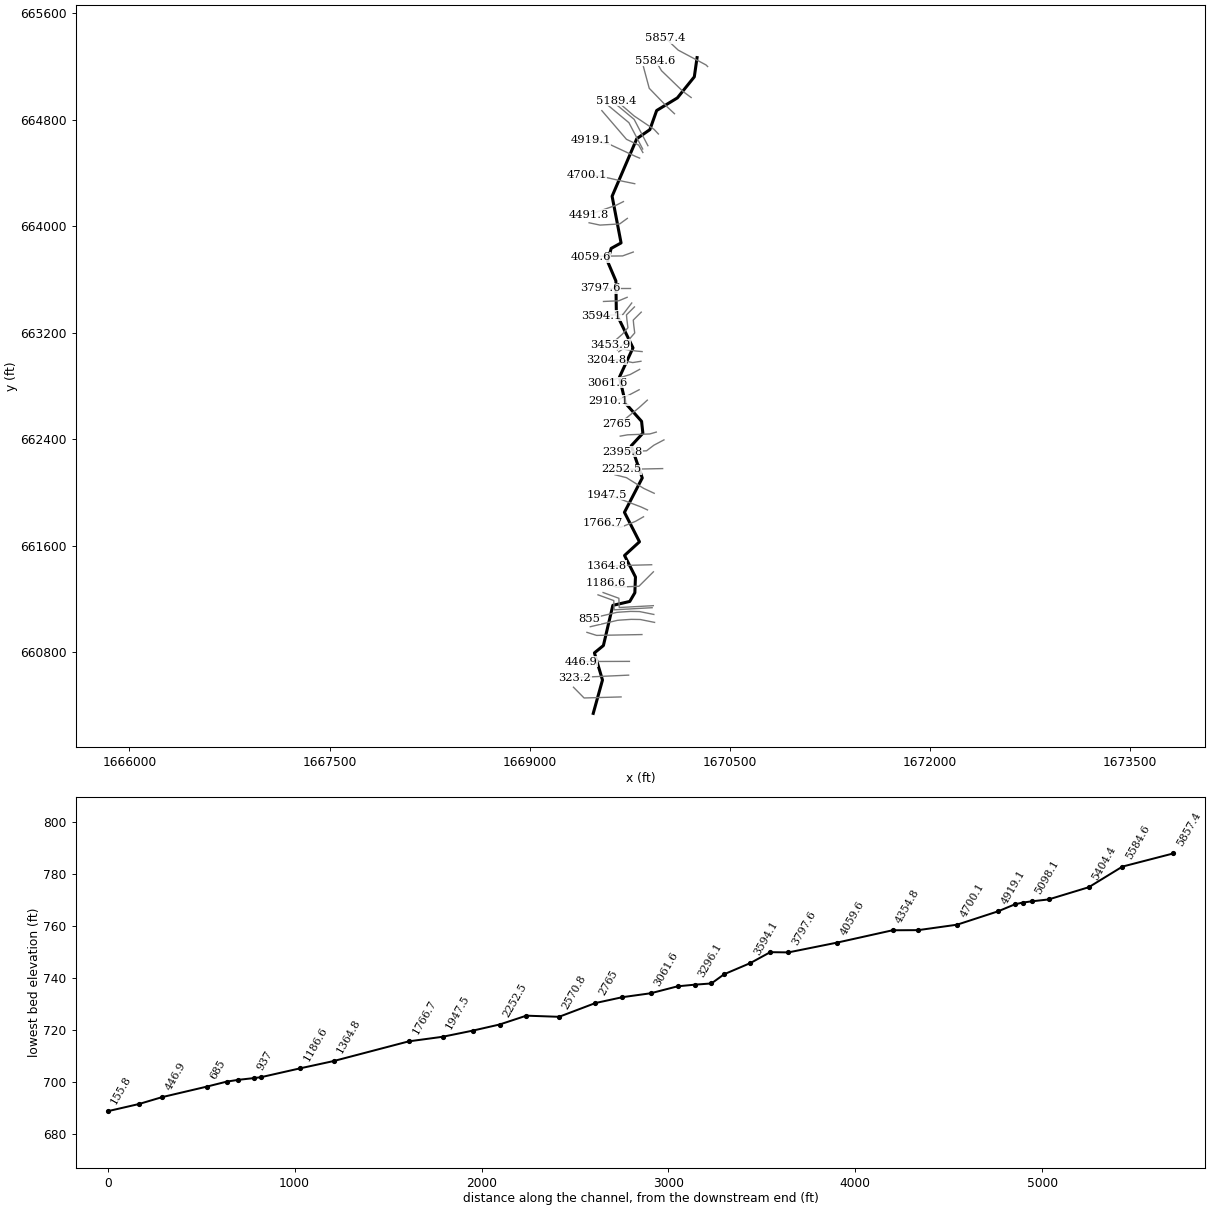
--- BSLYRN.prj (project) ---

Proj Title=BSLYRN
Current Plan=p01
Default Exp/Contr=0,0
English Units
Geom File=g01
Flow File=f01
Plan File=p01
BEGIN DESCRIPTION:
END DESCRIPTION:
DSS Export Rating Curves= 0
DSS Export Rating Curve Sorted= 0
DSS Export Volume Flow Curves= 0
DXF Filename=..\..\..\..\..\Engineering\Hydraulics\BSLYRN\BSLYRN.
DXF OffsetX= 0
DXF OffsetY= 0
DXF ScaleX= 0
DXF ScaleY= 0

--- BSLYRN.p01 (plan) ---

Plan Title=Floodplain
Program Version=4.00
Geom File=g01
Flow File=f01
K Sum by GR=0
Std Step Tol=0.01
Critical Tol=0.01
Num of Std Step Trials=20
Max Error Tol=0.3
Flow Tol Ratio=0.001
Split Flow NTrial=30
Split Flow Tol=0.02
Split Flow Ratio=0.02
Log Output Level=0
Friction Slope Method=1
Unsteady Friction Slope Method=2
Unsteady Bridges Friction Slope Method=1
Global Log Level=0
CheckData=False
Run HTab=0
Run UNet=0
Run PostProcess=0
UNET Theta=0
UNET Theta Warmup=0
UNET ZTol=0
UNET ZSATol=0
UNET MxIter=0
UNET MaxInSteps=0
UNET DtIC=0
UNET DtMin=0
UNET MaxCRTS=0
UNET WFStab=0
UNET SFStab=0
UNET WFX=0
UNET SFX=0
UNET DSS MLevel=0
UNET DZMax Abort=0
UNET Convert EG Bridges=0
UNET Use Existing IB Tables=0
UNET Froude Limit=0
UNET Froude Power=0
Write IC File=0
Echo Input=False
Echo Output=False
Write Detailed=0

--- BSLYRN.f01 (steady flow) ---

Flow Title=NFF Regression Equation
Program Version=4.10
Number of Profiles= 1
Profile Names=P100yr
River Rch & RM=BSLYRN,Main            ,5857.4
905.1071
River Rch & RM=BSLYRN,Main            ,4059.6
965.0185
River Rch & RM=BSLYRN,Main            ,446.9
1068.201
Boundary for River Rch & Prof#=BSLYRN,Main            , 1
Up Type= 0
Dn Type= 3
Dn Slope=0.018
DSS Import GetInterval= 0
DSS Import GetPeak= 0
DSS Import FillOption= 0

--- BSLYRN.g01 (geometry) ---

Geom Title=2003 WVU SAMB 3 Meter DEM
Program Version=4.10

River Reach=BSLYRN          ,Main
Reach XY= 30
     1670253.479      665267.067     1670232.906      665122.536
     1670106.022      664964.417     1669950.714      664869.579
     1669900.066      664726.302     1669801.933      664658.117
     1669616.913      664225.943     1669684.042       663875.48
     1669609.968      663834.276     1669582.604      663737.076
     1669645.177      663590.314     1669648.857      663344.693
     1669773.367      663087.471     1669671.826       662867.18
     1669717.399         662671.     1669837.728       662535.72
      1669847.39      662446.651     1669760.411       662352.38
     1669842.867      662110.492     1669709.304      661852.388
     1669822.034      661631.325     1669710.055       661528.46
     1669791.927      661367.166     1669787.355      661248.478
     1669749.335      661183.374     1669622.425       661153.86
     1669551.678      660852.211     1669484.404      660797.089
     1669544.821       660593.27     1669475.602      660342.836

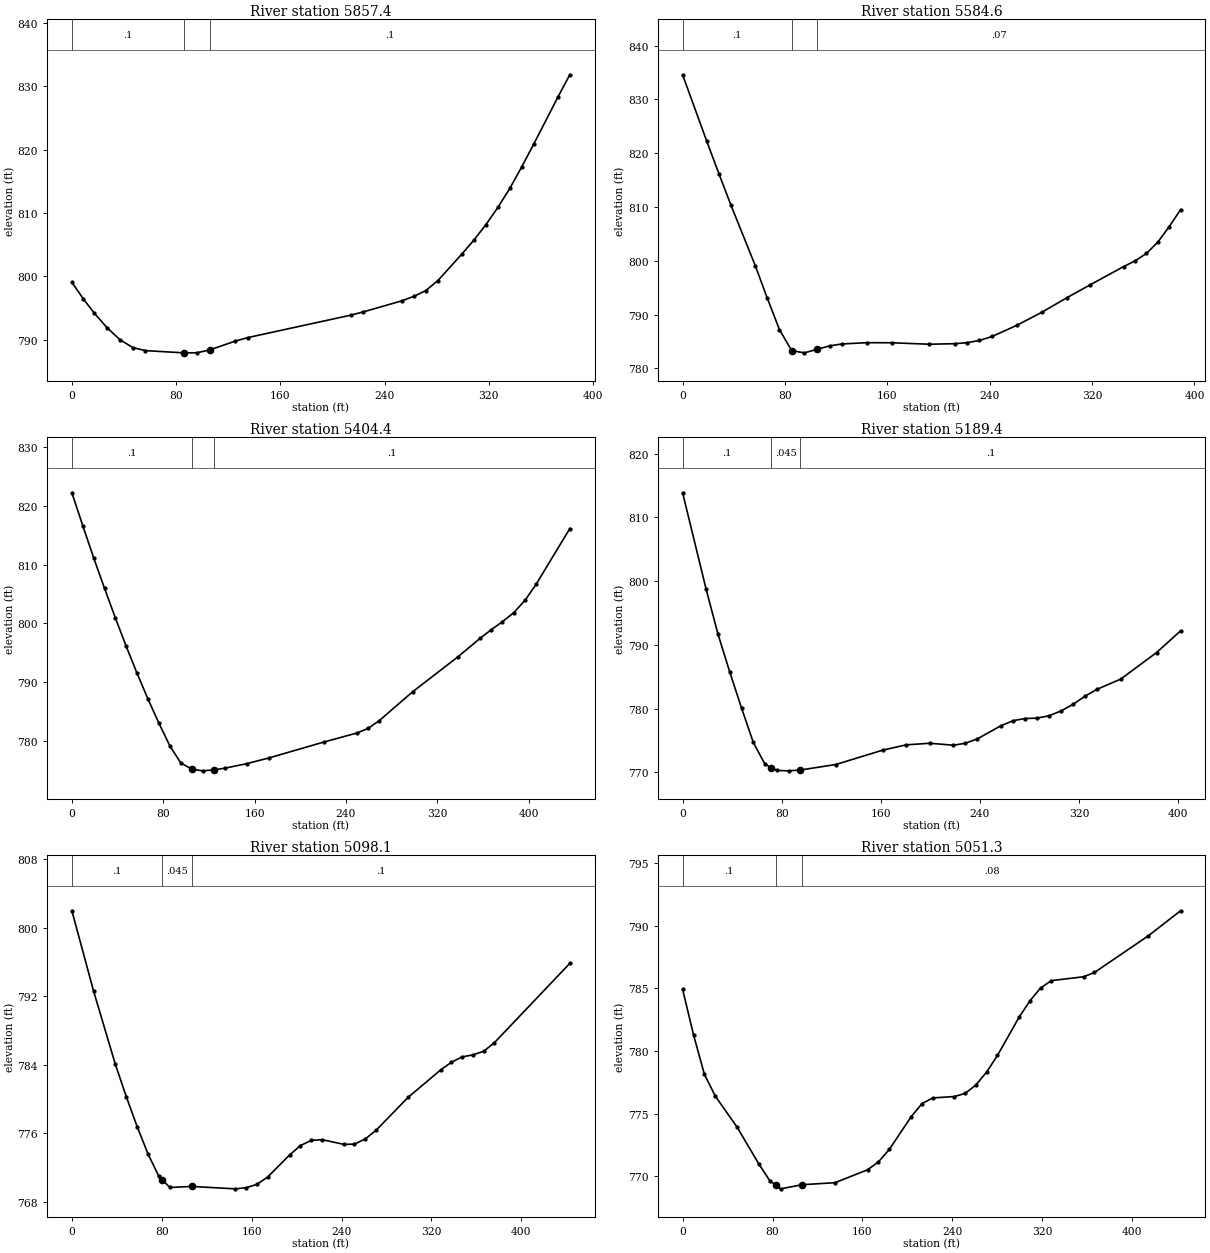
Type RM Length L Ch R = 1 ,5857.4  ,275.4,272.8,265.5
XS GIS Cut Line= 4
     1670332.588      665199.851     1670320.435      665212.004
     1670112.102      665323.115     1670018.352      665411.656
#Sta/Elev= 27
       0  799.09     8.6  796.52    17.2  794.22      27  791.92    36.9  790.04
    46.7   788.8    56.5  788.31    85.7  787.96    95.9  787.97   105.7  788.41
   125.4  789.81   135.2  790.37     214   793.9   223.8  794.42   253.3  796.16
   262.5  796.86   271.7  797.78   280.9  799.34   299.4  803.54   308.6  805.74
   317.8  808.17     327  810.88   336.2   813.9   345.4  817.32   354.6   820.9
     373  828.25   382.2   831.8
#Mann= 3 , 0 , 0
       0      .1       0    85.7    .045       0   105.7      .1       0
Bank Sta=85.7,105.7
XS Rating Curve= 0 ,0
Exp/Cntr=0.3,0.1

Type RM Length L Ch R = 1 ,5584.6  ,181.5,180.2,179
XS GIS Cut Line= 4
     1670209.324      664967.212      1670148.56      665012.351
     1669987.102      665168.601     1669941.963       665244.99
#Sta/Elev= 29
       0  834.57    18.9  822.19    28.4  816.16    37.8  810.31    56.8  799.08
    66.2  793.03    75.7  787.18    85.3  783.28    95.2  782.88     105  783.53
   114.8  784.17   124.5  784.53   144.1  784.77   163.6  784.75   192.9  784.48
   212.5  784.58   222.2  784.76     232  785.18   241.8  785.92   261.3  788.01
   280.8  790.43   300.4  793.14   318.1  795.47   344.7  798.92   353.6  799.98
   362.5  801.36   371.4  803.47   380.2  806.32   389.1  809.48
#Mann= 3 , 0 , 0
       0      .1       0    85.3    .045       0     105     .07       0
Bank Sta=85.3,105
XS Rating Curve= 0 ,0
Exp/Cntr=0.3,0.1

Type RM Length L Ch R = 1 ,5404.4  ,211.1,215,218.1
XS GIS Cut Line= 4
     1670084.324      664845.684     1670028.769      664897.767
     1669895.088      665036.656     1669851.685      665198.115
#Sta/Elev= 30
       0  822.24     9.5  816.67      19  811.21    28.6  805.98    38.1  800.94
    47.6  796.12    57.1  791.52    66.6  787.18    76.2  783.05    85.8  779.18
    95.4  776.27   105.4   775.2   114.7  774.93   124.3   775.1     134  775.38
   153.3  776.16   172.5  777.12   220.7  779.83   249.6  781.36   259.3  782.14
   268.9  783.42   298.4  788.37   337.8  794.28   357.4  797.45   367.3  798.94
   377.1   800.3   386.9  801.82   396.8  803.92   406.6  806.66   436.1  816.14
#Mann= 3 , 0 , 0
       0      .1       0   105.4    .045       0   124.3      .1       0
Bank Sta=105.4,124.3
XS Rating Curve= 0 ,0
Exp/Cntr=0.3,0.1

Type RM Length L Ch R = 1 ,5189.4  ,100.7,91.3,80.3
XS GIS Cut Line= 4
     1669963.665      664693.557     1669931.112       664728.28
     1669781.373      664829.191     1669650.079      664943.123
#Sta/Elev= 30
       0  813.86      19  798.71    28.6  791.65    38.1  785.71    47.6  780.06
    57.1  774.67    66.6  771.23    71.7  770.72    76.1  770.28    85.6  770.22
    95.1  770.35   123.6  771.21   161.6  773.47   180.6   774.3   199.6  774.55
   218.7  774.24   228.2  774.55   237.8  775.22   257.1  777.31   266.8  778.09
   276.4  778.43   286.1  778.49   295.8  778.86   305.4  779.61   315.1  780.64
   324.7  781.91   334.4     783   353.7  784.62   382.7  788.79     402  792.18
#Mann= 3 , 0 , 0
       0      .1       0    71.7    .045       0    95.1      .1       0
Bank Sta=71.7,95.1
XS Rating Curve= 0 ,0
Exp/Cntr=0.3,0.1

Type RM Length L Ch R = 1 ,5098.1  ,50.9,46.8,46.7
XS GIS Cut Line= 3
     1669885.106      664605.667     1669782.024      664803.149
     1669612.753      664944.208
#Sta/Elev= 30
       0  801.96    19.4  792.54    38.7  784.02    48.4  780.26    58.1  776.74
    67.8  773.54    77.5  770.93    80.4  770.54    87.2  769.64   106.5  769.76
   145.3  769.48     155  769.61   164.6     770   174.3  770.86   193.7  773.43
   203.4  774.53   213.1  775.15   222.8  775.22   241.9  774.68   251.5   774.7
   261.1  775.31   270.7  776.32   299.4  780.19   328.2  783.37   337.7  784.26
   347.3  784.89   356.9  785.13   366.5  785.55     376  786.55   443.1  795.81
#Mann= 3 , 0 , 0
       0      .1       0    80.4    .045       0   106.5      .1       0
Bank Sta=80.4,106.5
XS Rating Curve= 0 ,0
Exp/Cntr=0.3,0.1

Type RM Length L Ch R = 1 ,5051.3  ,22.4,41.6,56.5
XS GIS Cut Line= 3
     1669846.043       664580.71     1669742.961      664778.193
     1669573.691      664919.252
#Sta/Elev= 30
       0  784.92     9.7  781.29    19.4  778.14    29.1   776.4    48.4  773.94
    67.8     771    77.5  769.67    82.9   769.3    87.2  769.01   106.5  769.34
   135.6   769.5   164.6  770.53   174.3  771.16     184  772.16   203.4  774.76
   213.1  775.81   222.8  776.26   241.9  776.37   251.5  776.62   261.1   777.3
   270.7  778.34   280.2  779.65   299.4  782.69     309  783.99   318.6  785.03
   328.2  785.61   356.9  785.92   366.5  786.26   414.4  789.18   443.1  791.18
#Mann= 3 , 0 , 0
       0      .1       0    82.9    .045       0   106.5     .08       0
Bank Sta=82.9,106.5
XS Rating Curve= 0 ,0
Exp/Cntr=0.3,0.1

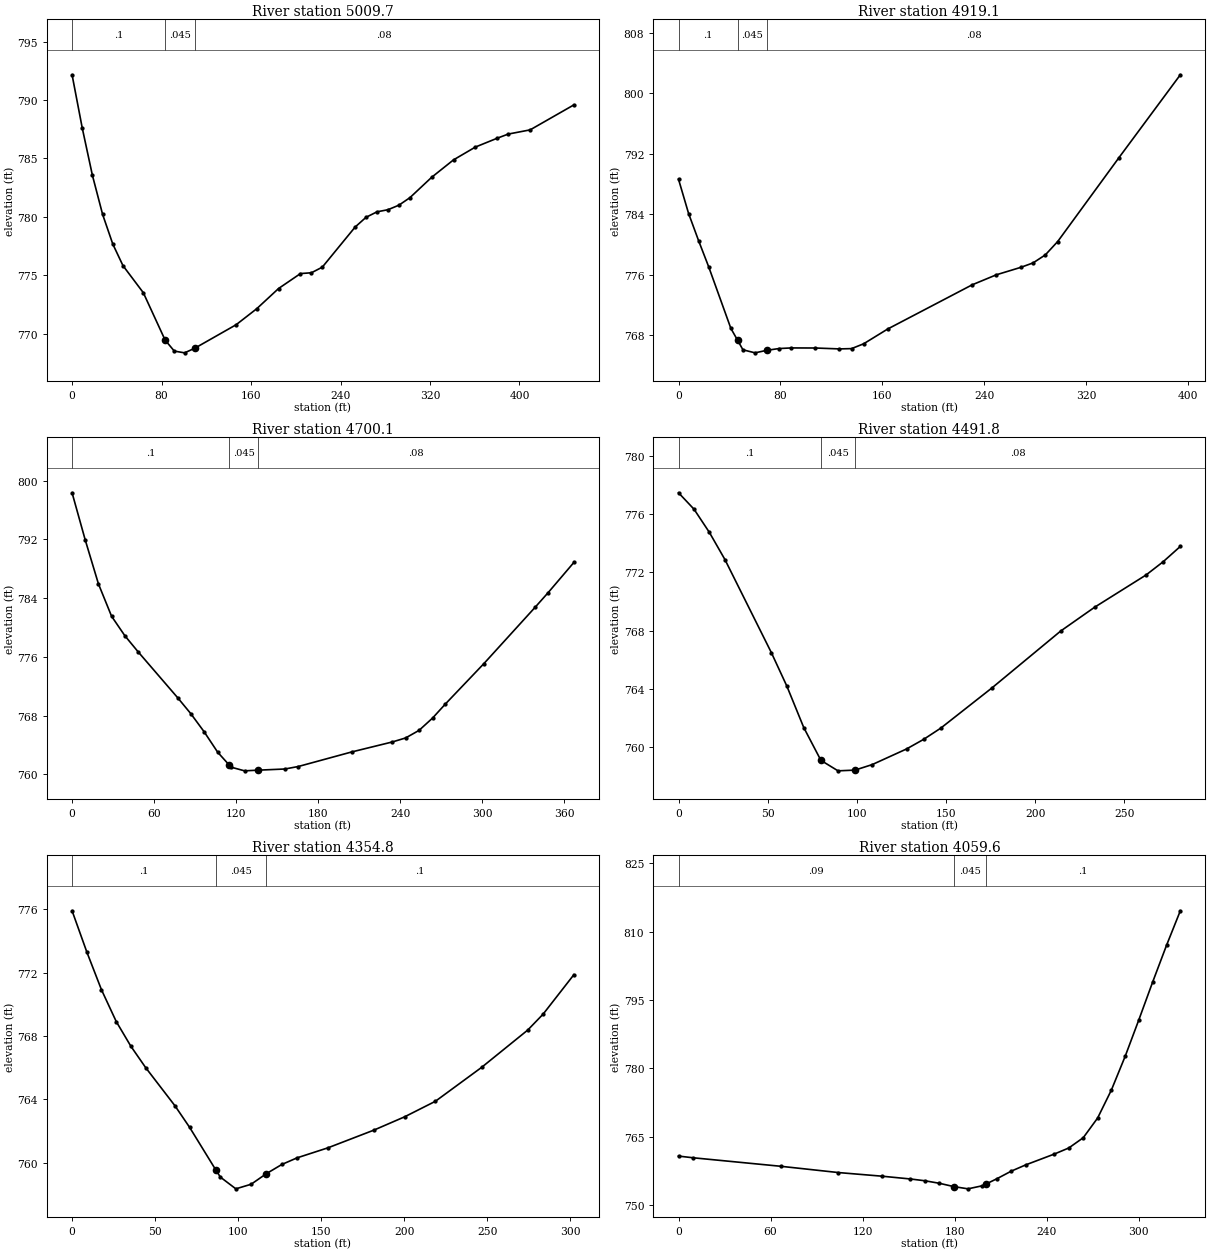
Type RM Length L Ch R = 1 ,5009.7  ,90.2,90.5,90.3
XS GIS Cut Line= 4
     1669847.345      664554.451     1669816.095      664610.007
     1669724.515       664653.41     1669540.053      664868.688
#Sta/Elev= 30
       0  792.17     9.1  787.61    18.2  783.55    27.3  780.21    36.4  777.67
    45.5  775.82    63.7   773.5    83.2  769.44    91.4   768.5   100.6  768.35
   109.8  768.75   146.7  770.76   165.1  772.13   184.6  773.86   204.2  775.14
     214  775.21   223.7  775.69   253.1  779.13   262.8  779.96   272.6  780.43
   282.4  780.61   292.2     781     302  781.64   321.5  783.39     341  784.88
   360.6  785.98   380.2  786.74   389.9  787.09   409.5  787.45   448.6  789.59
#Mann= 3 , 0 , 0
       0      .1       0    83.2    .045       0   109.8     .08       0
Bank Sta=83.2,109.8
XS Rating Curve= 0 ,0
Exp/Cntr=0.3,0.1

Type RM Length L Ch R = 1 ,4919.1  ,213.9,219.1,223.6
XS GIS Cut Line= 4
     1669823.257      664512.351      1669793.96      664524.287
     1669596.477      664616.517     1669455.418      664647.984
#Sta/Elev= 24
       0  788.63     7.9   784.1    15.8  780.48    23.7  777.03    41.1  768.88
    46.4   767.3    50.6  766.04    60.1  765.64    69.5  765.98      79  766.21
    88.5  766.29   107.4  766.28   126.4  766.16   135.9   766.2   145.4  766.84
   164.3   768.8   230.6  774.65   249.6  775.98   268.9  776.97   278.5  777.56
   288.1  778.62   297.8  780.39   345.9   791.5   394.1  802.48
#Mann= 3 , 0 , 0
       0      .1       0    46.4    .045       0    69.5     .08       0
Bank Sta=46.4,69.5
XS Rating Curve= 0 ,0
Exp/Cntr=0.3,0.1

Type RM Length L Ch R = 1 ,4700.1  ,195.3,208.2,220.6
XS GIS Cut Line= 4
     1669786.581      664320.076     1669701.512      664337.438
     1669529.203      664376.717     1669426.121      664384.313
#Sta/Elev= 26
       0  798.36     9.6  791.95    19.3  785.94    28.9  781.54    38.6  778.89
    48.2  776.72    77.2  770.45    86.8  768.28    96.6   765.8   106.5  763.02
   115.1  761.24   116.3  760.99   126.1  760.49   135.9  760.58   155.6  760.74
   165.4  761.08   204.6  763.07   234.1  764.42   243.9  764.97   253.7     766
   263.6  767.68     273   769.6   301.1  775.09   338.7  782.79   348.1  784.76
   366.9  788.87
#Mann= 3 , 0 , 0
       0      .1       0   115.1    .045       0   135.9     .08       0
Bank Sta=115.1,135.9
XS Rating Curve= 0 ,0
Exp/Cntr=0.3,0.1

Type RM Length L Ch R = 1 ,4491.8  ,142.8,137,130
XS GIS Cut Line= 3
     1669701.729      664185.745     1669647.475      664158.618
     1669439.142      664085.918
#Sta/Elev= 20
       0  777.47     8.7  776.34    17.3  774.75      26  772.89      52  766.51
    60.7  764.21    70.2  761.36    79.8  759.11    89.4  758.39    98.9  758.44
   108.6  758.82   127.8  759.89   137.4  760.55     147  761.32   175.8  764.09
   214.2  767.98   233.3  769.62   262.1  771.83   271.7  772.74   281.3  773.79
#Mann= 3 , 0 , 0
       0      .1       0    79.8    .045       0    98.9     .08       0
Bank Sta=79.8,98.9
XS Rating Curve= 0 ,0
Exp/Cntr=0.3,0.1

Type RM Length L Ch R = 1 ,4354.8  ,296.3,295.2,289.6
XS GIS Cut Line= 4
     1669731.026       664059.66     1669673.734      664017.993
     1669526.165      664009.313     1669444.567      664026.674
#Sta/Elev= 23
       0  775.91     8.9   773.3    17.7  770.92    26.6  768.91    35.4  767.35
    44.3     766      62  763.58    70.8  762.22    86.5  759.54    89.3  759.08
    98.6  758.34   107.8  758.63     117   759.3   126.3  759.88   135.5   760.3
     154  760.93   181.7  762.05   200.2  762.89   218.7  763.87   246.5  766.01
   274.3  768.37   283.6  769.38   302.1  771.87
#Mann= 3 , 0 , 0
       0      .1       0    86.5    .045       0     117      .1       0
Bank Sta=86.5,117
XS Rating Curve= 0 ,0
Exp/Cntr=0.3,0.1

Type RM Length L Ch R = 1 ,4059.6  ,261.8,262.1,261.2
XS GIS Cut Line= 4
     1669775.514      663807.056     1669695.218      663777.759
     1669507.501      663775.589     1669454.333      663766.908
#Sta/Elev= 25
       0  760.79     9.5  760.42    66.5  758.56   104.2  757.18   132.4  756.39
   151.2  755.77   160.6  755.38     170  754.83   179.3  754.11   188.7  753.61
   198.1  754.29   200.4  754.66   207.5  755.82   216.9  757.49   226.3  758.86
     245  761.24   254.4  762.57   263.8  764.81   273.2  769.14   282.2   775.3
   291.2  782.71   300.1   790.7   309.1  798.98   318.1  806.99   327.1  814.57
#Mann= 3 , 0 , 0
       0     .09       0   179.3    .045       0   200.4      .1       0
Bank Sta=179.3,200.4
XS Rating Curve= 0 ,0
Exp/Cntr=0.3,0.1

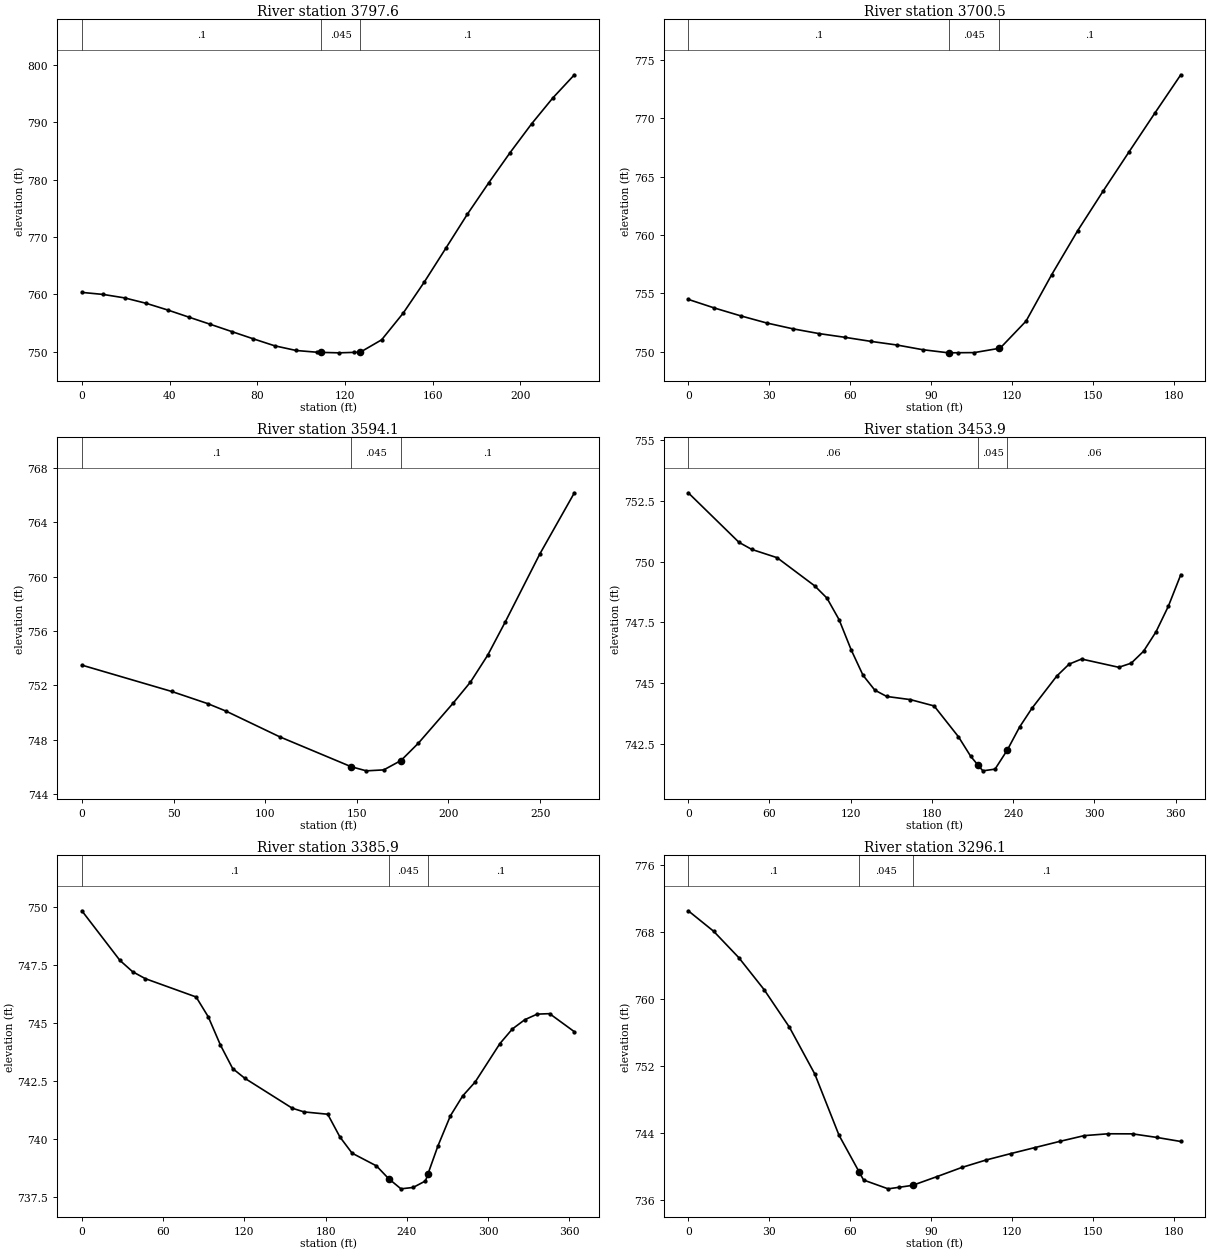
Type RM Length L Ch R = 1 ,3797.6  ,96,97.1,97.7
XS GIS Cut Line= 2
     1669751.642      663533.618     1669527.033      663533.618
#Sta/Elev= 26
       0  760.34     9.8  759.98    19.5  759.38    29.3  758.44    39.1  757.28
    48.8  756.03    58.6  754.78    68.4  753.51    78.1  752.26    87.9  751.04
    97.7  750.22   107.4  749.91   109.1  749.89   117.2  749.81   124.1  749.89
     127  749.93   136.7  752.08   146.5  756.71   156.2  762.17     166  768.05
   175.8  773.96   185.6  779.46   195.3   784.7   205.1  789.71   214.8  794.23
   224.6  798.25
#Mann= 3 , 0 , 0
       0      .1       0   109.1    .045       0     127      .1       0
Bank Sta=109.1,127
XS Rating Curve= 0 ,0
Exp/Cntr=0.3,0.1

Type RM Length L Ch R = 1 ,3700.5  ,106.3,106.4,106.5
XS GIS Cut Line= 3
     1669729.512      663467.031     1669667.012      663440.989
     1669552.429      663435.781
#Sta/Elev= 22
       0  754.48     9.7  753.74    19.4  753.07      29  752.46    38.7  751.96
    48.4  751.55      58  751.23    67.7  750.88    77.3  750.57    86.8  750.17
    96.4   749.9     100  749.91   105.9  749.92     115  750.28   115.5   750.3
   125.1  752.62   134.6   756.6   144.2  760.36   153.7  763.78   163.3  767.14
   172.8  770.44   182.4  773.72
#Mann= 3 , 0 , 0
       0      .1       0    96.4    .045       0     115      .1       0
Bank Sta=96.4,115
XS Rating Curve= 0 ,0
Exp/Cntr=0.3,0.1

Type RM Length L Ch R = 1 ,3594.1  ,121.5,140.3,158.4
XS GIS Cut Line= 3
     1669764.012      663424.243     1669698.474      663338.523
     1669537.883      663329.842
#Sta/Elev= 16
       0  753.49      49  751.55    68.7  750.65    78.5  750.11   107.9  748.21
     147     746   155.2   745.7   164.7  745.77   174.1  746.46   183.6  747.74
   202.5  750.68     212  752.24   221.4  754.22   230.9  756.65   249.8  761.67
   268.7  766.19
#Mann= 3 , 0 , 0
       0      .1       0     147    .045       0   174.1      .1       0
Bank Sta=147,174.1
XS Rating Curve= 0 ,0
Exp/Cntr=0.3,0.1

Type RM Length L Ch R = 1 ,3453.9  ,67.9,67.9,64.7
XS GIS Cut Line= 6
     1669784.194      663394.729     1669724.515       663335.05
      1669727.77      663299.243     1669735.366      663238.479
     1669694.133      663190.736     1669605.158      663111.526
#Sta/Elev= 30
       0  752.83    37.5  750.79    46.9   750.5    65.6  750.16    93.4     749
   102.4   748.5   111.4  747.61   120.4  746.36   129.1  745.32   137.8  744.71
   146.6  744.45   164.1  744.32   181.6  744.06   199.6  742.79   208.6  741.99
   213.8  741.64   217.6  741.39   226.6  741.46   235.7  742.25   244.7  743.19
   253.8  743.96   272.2  745.29   281.3  745.78   290.5  745.99     318  745.65
   327.2  745.82   336.3  746.31   345.5  747.11   354.6  748.16   363.8  749.46
#Mann= 3 , 0 , 0
       0     .06       0   213.8    .045       0   235.7     .06       0
Bank Sta=213.8,235.7
XS Rating Curve= 0 ,0
Exp/Cntr=0.3,0.1

Type RM Length L Ch R = 1 ,3385.9  ,112.8,89.8,69.7
XS GIS Cut Line= 6
     1669835.192      663355.667     1669775.514      663295.988
     1669778.769      663260.181     1669786.364      663199.417
     1669745.132      663151.674     1669656.156      663072.464
#Sta/Elev= 30
       0  749.85    28.1  747.71    37.5  747.22    46.9  746.92    84.4  746.13
    93.4  745.27   102.4  744.05   111.4  743.04   120.4  742.62   155.4  741.33
   164.1  741.17   181.6  741.07   190.6  740.09   199.6  739.39   217.6  738.84
   226.6  738.29   235.7  737.85   244.7  737.91   253.8  738.19   255.5  738.47
     263   739.7   272.2     741   281.3  741.86   290.5  742.46   308.8  744.12
     318  744.75   327.2  745.15   336.3  745.39   345.5  745.41   363.8  744.63
#Mann= 3 , 0 , 0
       0      .1       0   226.6    .045       0   255.5      .1       0
Bank Sta=226.6,255.5
XS Rating Curve= 0 ,0
Exp/Cntr=0.3,0.1

Type RM Length L Ch R = 1 ,3296.1  ,92.2,91.3,90
XS GIS Cut Line= 4
     1669841.703      663059.443     1669795.045      663063.783
     1669696.303      663078.974     1669667.007      663058.358
#Sta/Elev= 23
       0  770.55     9.4  768.11    18.7  764.97    28.1  761.15    37.5  756.66
    46.9  751.08    55.9  743.76    63.3  739.42      65  738.42    74.1  737.37
    78.3  737.56    83.2  737.79    92.3  738.84   101.4  739.92   110.4  740.81
   119.5  741.57   128.6   742.3   137.7  743.03   146.8  743.72   155.7  743.94
   164.7  743.93   173.6  743.51   182.6  743.02
#Mann= 3 , 0 , 0
       0      .1       0    63.3    .045       0    83.2      .1       0
Bank Sta=63.3,83.2
XS Rating Curve= 0 ,0
Exp/Cntr=0.3,0.1

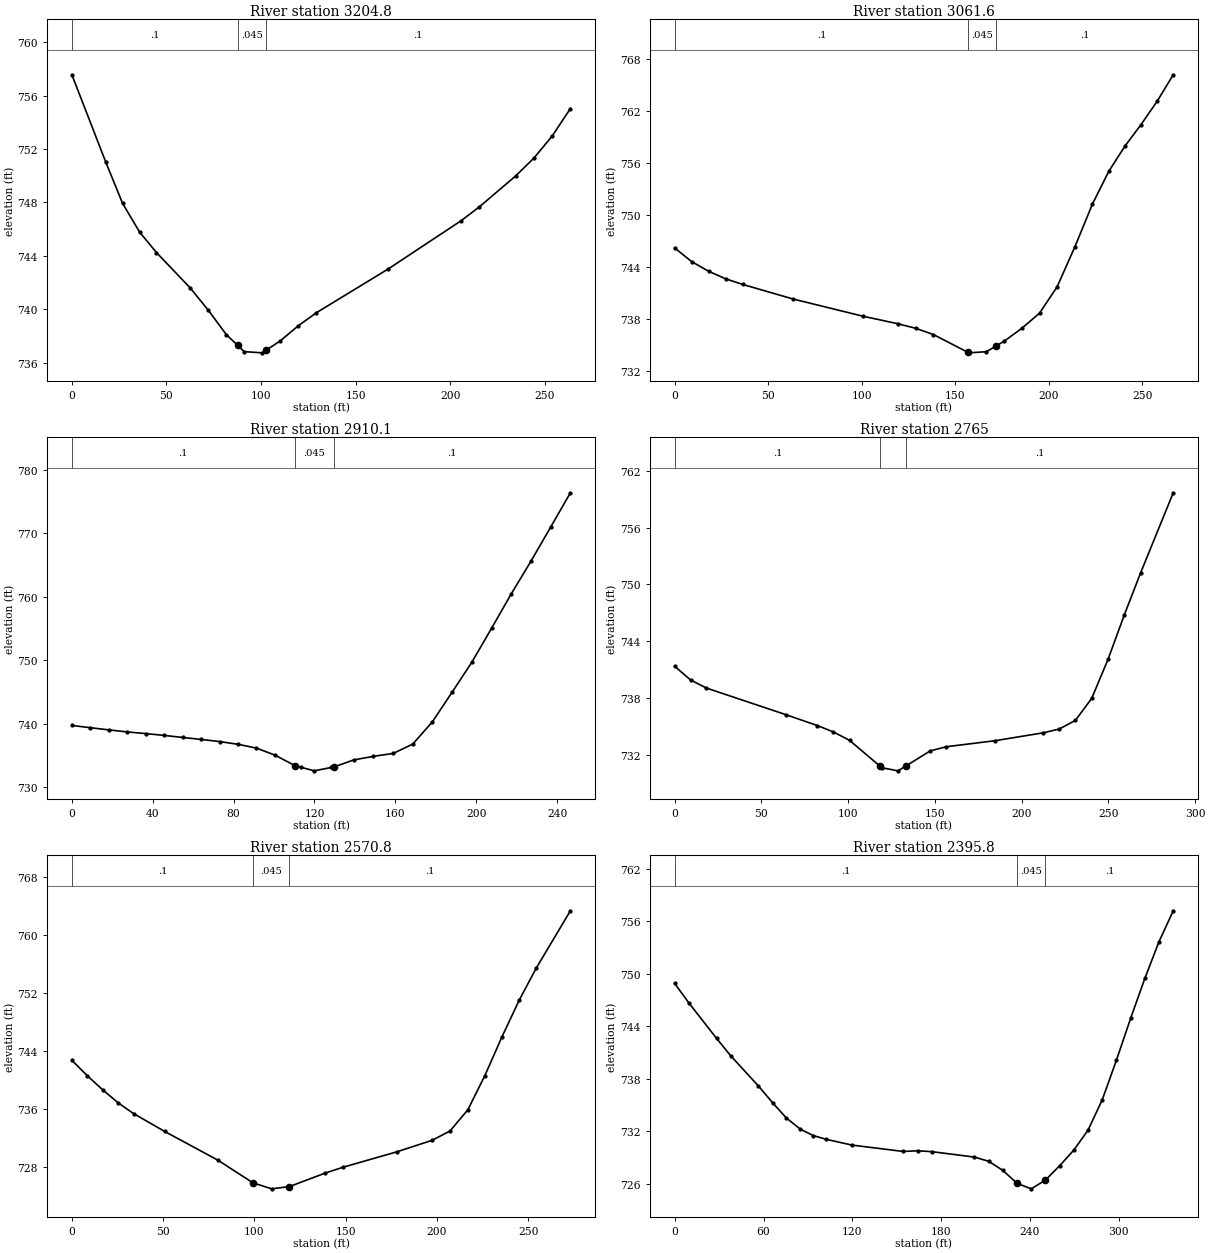
Type RM Length L Ch R = 1 ,3204.8  ,130.5,143.2,154.1
XS GIS Cut Line= 4
     1669833.022      662986.743     1669771.173      662976.978
     1669659.411      662999.764     1669572.606      662997.594
#Sta/Elev= 22
       0  757.56    17.9  751.02    26.8  747.93    35.8  745.78    44.7  744.25
    62.6  741.59    72.1  739.93    81.6  738.11    87.6   737.3    91.1  736.83
   100.6  736.74   102.6  736.93   110.1  737.63   119.6  738.76   129.2  739.74
   167.2  743.02   205.6  746.62   215.3  747.66   234.6  749.99   244.2  751.32
   253.9  752.98   263.5  755.03
#Mann= 3 , 0 , 0
       0      .1       0    87.6    .045       0   102.6      .1       0
Bank Sta=87.6,102.6
XS Rating Curve= 0 ,0
Exp/Cntr=0.3,0.1

Type RM Length L Ch R = 1 ,3061.6  ,149.5,151.5,154
XS GIS Cut Line= 4
     1669823.257      662925.979     1669751.642      662886.917
     1669616.008      662845.684     1669576.946      662827.238
#Sta/Elev= 25
       0  746.16     9.1  744.58    18.1  743.48    27.2  742.61    36.3  741.96
    63.4  740.27   100.5   738.3   119.4  737.42   128.8   736.9   138.3  736.18
   156.8  734.12   157.2  734.07   166.6   734.2   171.8  734.86   176.1  735.41
   185.5  736.89     195  738.64   204.4  741.68   213.9  746.29   223.3  751.23
     232  754.99   240.6  757.89   249.3   760.4   257.9  763.09   266.5  766.14
#Mann= 3 , 0 , 0
       0      .1       0   156.8    .045       0   171.8      .1       0
Bank Sta=156.8,171.8
XS Rating Curve= 0 ,0
Exp/Cntr=0.3,0.1

Type RM Length L Ch R = 1 ,2910.1  ,137.3,145,148.6
XS GIS Cut Line= 4
     1669819.567      662772.984     1669730.592      662726.326
     1669640.531      662689.434     1669591.703      662689.434
#Sta/Elev= 29
       0  739.71     9.1  739.36    18.3  739.01    27.4  738.69    36.5  738.43
    45.7  738.14    54.8  737.82    63.9  737.51    73.1  737.17    82.2  736.74
    91.3  736.14   100.5  735.03   110.2   733.4   113.4  733.12   119.9  732.56
   128.4   733.1   129.7  733.18   139.4  734.28   149.1  734.84   158.9   735.3
   168.6  736.77   178.3  740.27   188.1  744.96   197.8  749.65   207.6  755.02
   217.3  760.42   227.1   765.6   236.8  770.94   246.6  776.37
#Mann= 3 , 0 , 0
       0      .1       0   110.2    .045       0   129.7      .1       0
Bank Sta=110.2,129.7
XS Rating Curve= 0 ,0
Exp/Cntr=0.3,0.1

Type RM Length L Ch R = 1 ,2765    ,207.1,194.3,181.3
XS GIS Cut Line= 4
     1669880.765      662694.859     1669820.001      662639.521
     1669704.984       662545.12     1669656.156      662516.908
#Sta/Elev= 22
       0  741.34     9.1   739.9    18.3  739.04    63.9  736.24    82.2  735.08
    91.5   734.4   100.8  733.51   118.5  730.76   119.4  730.62   128.7  730.29
   133.5  730.83   147.3   732.4   156.6  732.84   184.5  733.47   212.4  734.31
   221.7  734.71     231  735.63   240.4  737.95   249.8  742.08   259.2  746.78
   268.6  751.23   287.4  759.69
#Mann= 3 , 0 , 0
       0      .1       0   118.5    .045       0   133.5      .1       0
Bank Sta=118.5,133.5
XS Rating Curve= 0 ,0
Exp/Cntr=0.3,0.1

Type RM Length L Ch R = 1 ,2570.8  ,175.7,175,170.9
XS GIS Cut Line= 4
      1669948.04      662455.059     1669899.211      662440.953
     1669733.196      662434.443     1669677.857      662424.677
#Sta/Elev= 21
       0  742.71     8.5  740.57    16.9  738.64    25.4  736.84    33.9  735.35
    50.8  732.91    80.1  728.93    99.2  725.82   109.5  724.99   119.2   725.3
   138.8  727.16   148.6  727.97   177.9  730.08   197.4  731.68   207.2  732.96
     217  735.89   226.3  740.59   235.7  745.95   245.1  750.98   254.4  755.39
   273.2  763.33
#Mann= 3 , 0 , 0
       0      .1       0    99.2    .045       0   119.2      .1       0
Bank Sta=99.2,119.2
XS Rating Curve= 0 ,0
Exp/Cntr=0.3,0.1

Type RM Length L Ch R = 1 ,2395.8  ,141.9,143.3,146.3
XS GIS Cut Line= 4
     1670005.331      662396.465     1669930.273      662356.714
     1669874.906      662314.434     1669692.614      662306.839
#Sta/Elev= 29
       0   748.9     9.4  746.71    28.3  742.62    37.8  740.64    56.6  737.18
    66.1  735.28    75.5  733.52    84.9  732.25    93.6  731.52   102.4  731.09
   119.8  730.43   154.6   729.7   164.2  729.78   173.8  729.68   202.6  729.06
   212.2  728.58   221.8  727.54   231.4  726.06     241  725.43   250.6  726.43
   260.2  728.07   269.8  729.86   279.4  732.14     289   735.6   298.6  740.14
   308.2  744.92   317.8  749.48   327.4  753.69     337  757.21
#Mann= 3 , 0 , 0
       0      .1       0   231.4    .045       0   250.6      .1       0
Bank Sta=231.4,250.6
XS Rating Curve= 0 ,0
Exp/Cntr=0.3,0.1

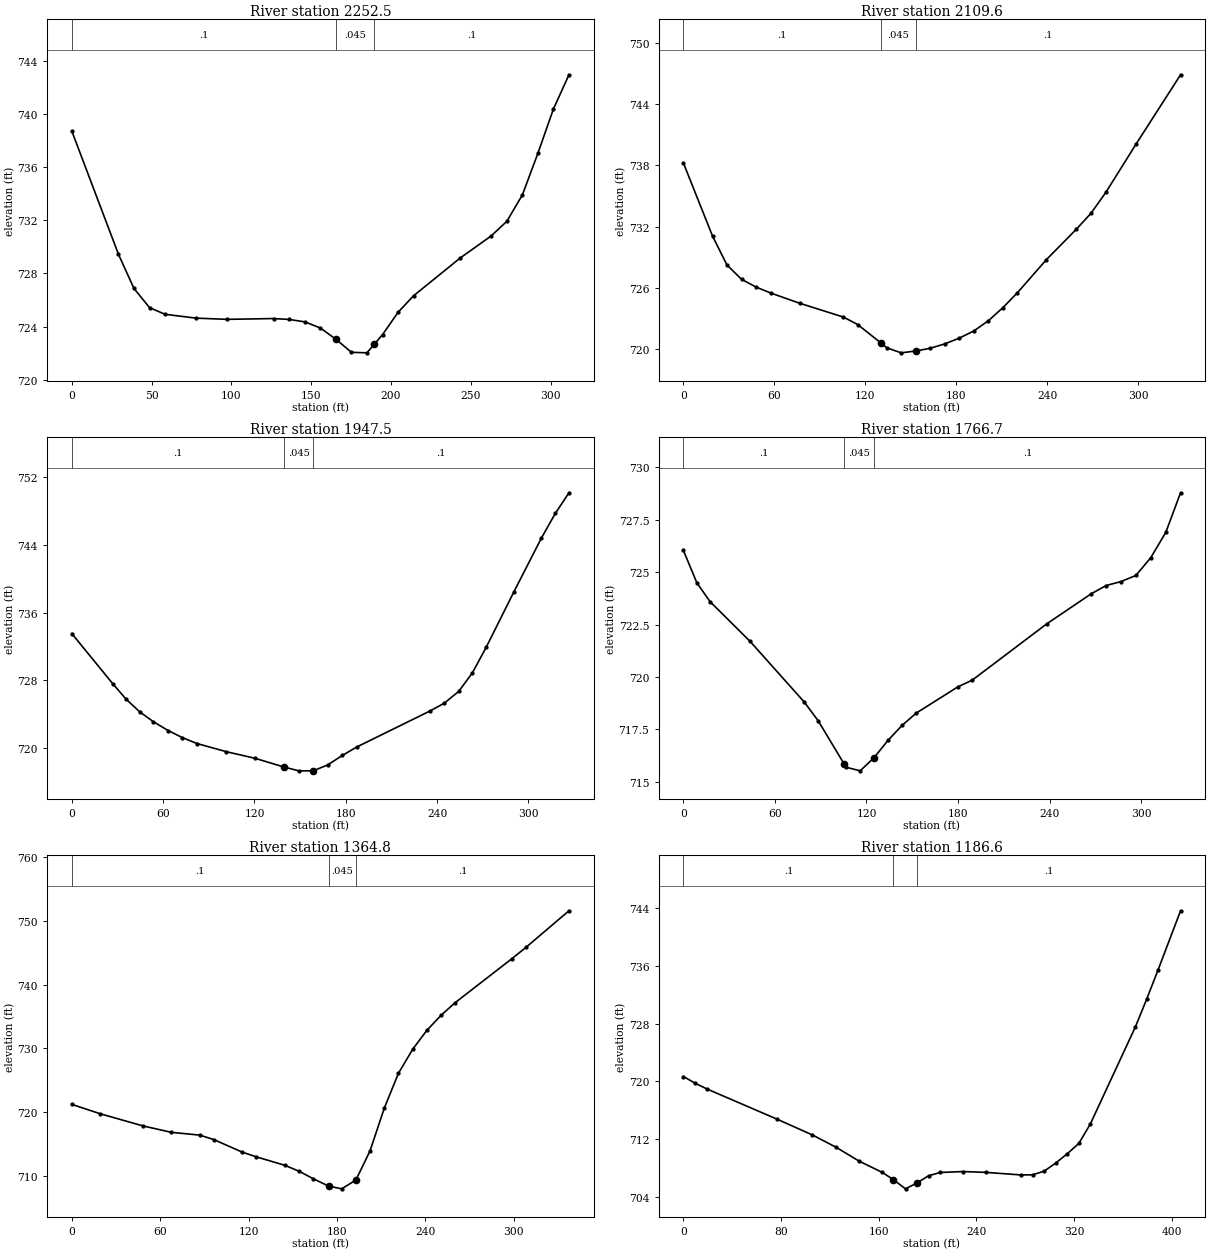
Type RM Length L Ch R = 1 ,2252.5  ,154.9,142.9,130.1
XS GIS Cut Line= 2
     1669995.566      662180.971     1669684.151       662174.46
#Sta/Elev= 25
       0   738.7    29.2  729.44    38.9  726.87    48.7  725.42    58.4  724.92
    77.9  724.63    97.3  724.54   126.5   724.6   136.3  724.53     146  724.35
   155.7  723.89   165.5  723.04   175.2  722.06   184.9  722.02   189.6  722.68
   194.7  723.39   204.4  725.07   214.1  726.31   243.4  729.16   262.8  730.82
   272.6  731.92   282.3   733.9     292  737.02   301.8  740.38   311.5  742.94
#Mann= 3 , 0 , 0
       0      .1       0   165.5    .045       0   189.6      .1       0
Bank Sta=165.5,189.6
XS Rating Curve= 0 ,0
Exp/Cntr=0.3,0.1

Type RM Length L Ch R = 1 ,2109.6  ,159,162.1,164.7
XS GIS Cut Line= 4
     1669932.415      661995.424      1669854.29      662031.882
     1669724.298      662112.828     1669638.578       662134.53
#Sta/Elev= 26
       0  738.22    19.2  731.08    28.7  728.26    38.3  726.86    47.9   726.1
    57.5  725.52    76.6  724.52   105.4  723.17   114.9  722.44     130  720.66
   134.1  720.16   143.6  719.67   153.2  719.85   162.8  720.12   172.4  720.55
   181.9  721.11   191.5  721.81   201.1  722.81   210.6  724.08   220.2  725.54
   239.4  728.79     259  731.74   268.8  733.32   278.6  735.37   298.3  740.04
   327.8  746.85
#Mann= 3 , 0 , 0
       0      .1       0     130    .045       0   153.2      .1       0
Bank Sta=130,153.2
XS Rating Curve= 0 ,0
Exp/Cntr=0.3,0.1

Type RM Length L Ch R = 1 ,1947.5  ,162.7,180.8,197.7
XS GIS Cut Line= 4
     1669882.067      661870.424     1669833.456      661892.993
     1669645.956      661964.174     1669576.512      661985.007
#Sta/Elev= 25
       0  733.52    26.8  727.61    35.7  725.75    44.7  724.25    53.6   723.1
    63.2  722.06    72.7  721.21    82.2  720.52   101.4  719.56   120.4  718.77
   139.6  717.73   149.1  717.29   158.6  717.29   168.2     718   177.8  719.12
   187.3  720.12     235  724.34   244.6  725.28   254.2  726.69   263.2  728.89
   272.3  731.93   290.4  738.45   308.5  744.82   317.6  747.72   326.6  750.17
#Mann= 3 , 0 , 0
       0      .1       0   139.6    .045       0   158.6      .1       0
Bank Sta=139.6,158.6
XS Rating Curve= 0 ,0
Exp/Cntr=0.3,0.1

Type RM Length L Ch R = 1 ,1766.7  ,409.1,401.9,387.9
XS GIS Cut Line= 4
     1669852.553      661819.208      1669791.79      661784.486
     1669681.112      661739.998     1669547.649      661769.295
#Sta/Elev= 23
       0  726.03     8.8  724.49    17.5  723.59    43.7   721.7    79.2  718.81
    88.3  717.92   105.5  715.84   106.7   715.7   115.9  715.53     125  716.16
   134.2  716.99   143.4   717.7   152.6  718.28   180.1  719.54   189.3  719.85
   238.1  722.53   267.4  723.97   277.1  724.36   286.9  724.55   296.6  724.84
   306.4  725.69   316.2  726.89   325.9  728.78
#Mann= 3 , 0 , 0
       0      .1       0   105.5    .045       0     125      .1       0
Bank Sta=105.5,125
XS Rating Curve= 0 ,0
Exp/Cntr=0.3,0.1

Type RM Length L Ch R = 1 ,1364.8  ,177.6,178.2,180.2
XS GIS Cut Line= 2
     1669913.317      661458.965     1669575.861      661450.068
#Sta/Elev= 24
       0  721.19    19.3  719.72    48.2  717.82    67.5  716.81    86.8  716.37
    96.4  715.67   115.7   713.7   125.4  712.95   144.7  711.63   154.3   710.7
     164  709.52   174.3  708.38   183.2  707.94   192.9  709.32   202.5  713.89
   212.2  720.61   221.8  726.07   231.5  729.85   241.1  732.81   250.8  735.18
   260.4  737.17     299  744.08   308.6  745.87   337.6  751.57
#Mann= 3 , 0 , 0
       0      .1       0   174.3    .045       0   192.9      .1       0
Bank Sta=174.3,192.9
XS Rating Curve= 0 ,0
Exp/Cntr=0.3,0.1

Type RM Length L Ch R = 1 ,1186.6  ,245.5,210.4,174
XS GIS Cut Line= 4
     1669926.338      661405.797     1669817.831       661297.29
     1669647.475       661290.78     1669570.435      661322.247
#Sta/Elev= 26
       0  720.68     9.6  719.75    19.2  718.96    76.7  714.78   105.5  712.61
   124.7  710.93   143.9  708.98   162.9  707.42   171.9  706.43   181.9  705.15
   191.3  705.96   200.8  706.96   210.3  707.41   229.2  707.54   248.2  707.42
   276.6  707.07     286  707.09   295.5   707.6     305  708.72   314.5  710.02
   323.9  711.43   333.2  714.08   370.2  727.54   379.4  731.35   388.7  735.38
   407.2  743.59
#Mann= 3 , 0 , 0
       0      .1       0   171.9    .045       0   191.3      .1       0
Bank Sta=171.9,191.3
XS Rating Curve= 0 ,0
Exp/Cntr=0.3,0.1

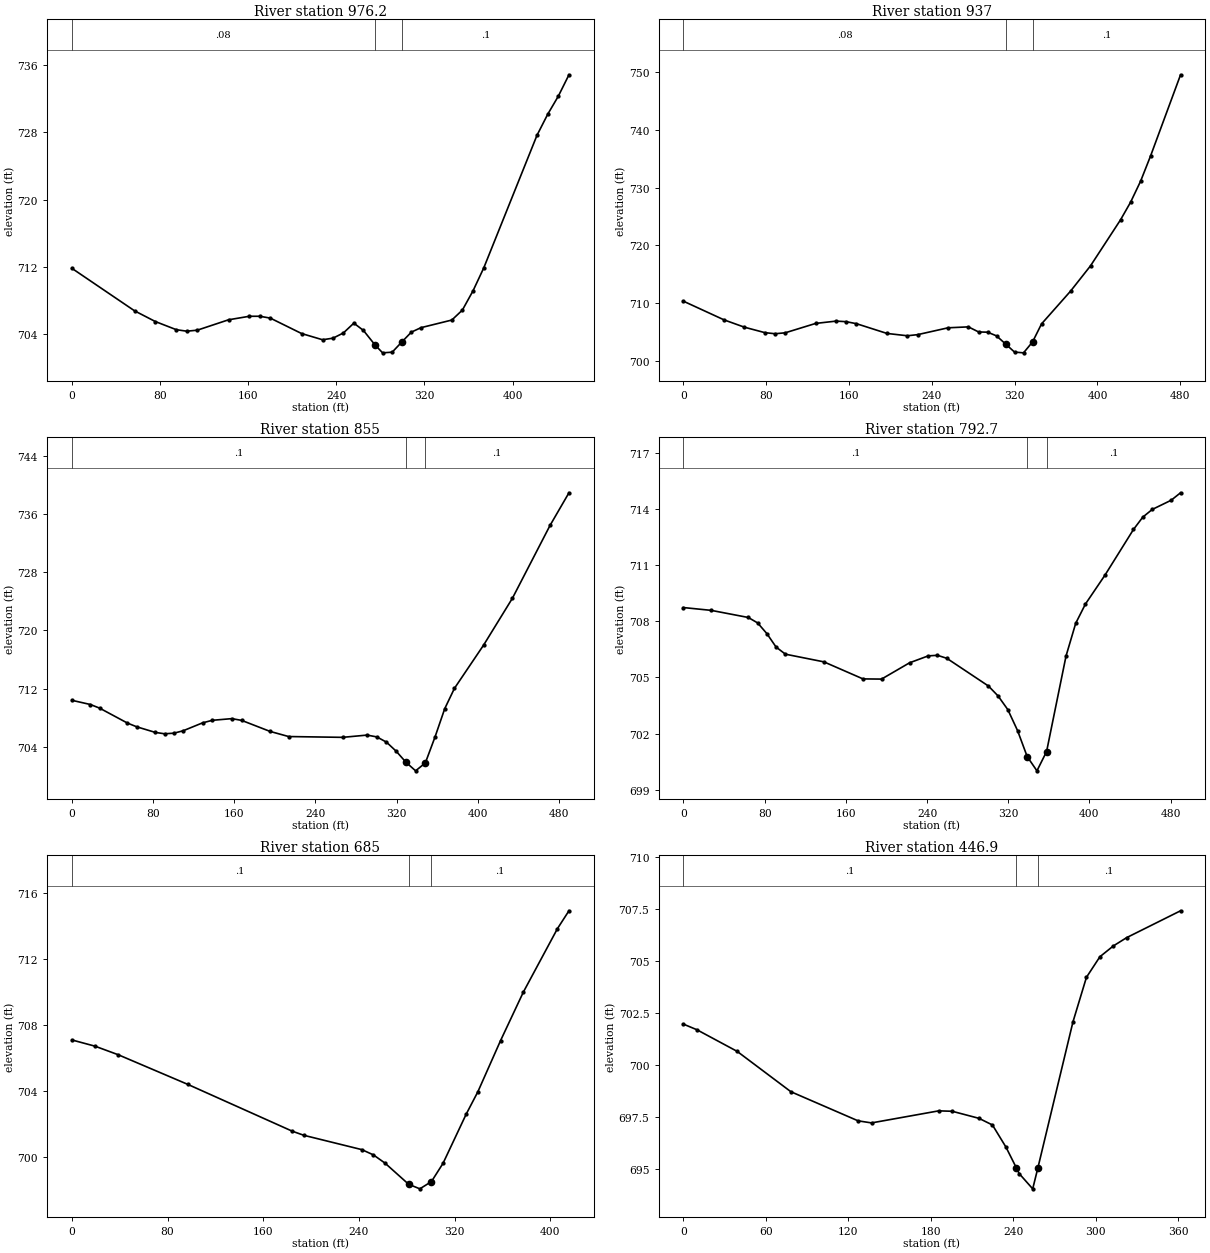
Type RM Length L Ch R = 1 ,976.2   ,48.1,39.2,39
XS GIS Cut Line= 4
     1669925.948      661151.638     1669670.392      661137.749
     1669667.614      661207.193     1669549.559      661250.249
#Sta/Elev= 30
       0   711.8    56.9  706.73    75.8  705.45    94.8  704.48   104.3   704.3
   113.8  704.42   142.2  705.66   161.1  706.08   170.6  706.08   180.1  705.86
   208.5  704.02   227.5  703.28     237  703.47   246.4  704.09   255.9  705.26
   264.6  704.39     275  702.68     282  701.72   290.7   701.8   299.4  703.01
   308.1  704.19   316.8  704.72   344.8  705.63   354.4  706.82   364.1  709.13
   373.8  711.85   422.1  727.66   431.8  730.16   441.4  732.31   451.1  734.87
#Mann= 3 , 0 , 0
       0     .08       0     275    .045       0   299.4      .1       0
Bank Sta=275,299.4
XS Rating Curve= 0 ,0
Exp/Cntr=0.3,0.1

Type RM Length L Ch R = 1 ,937     ,31.9,82,122.5
XS GIS Cut Line= 4
      1669916.92       661136.36     1669632.198      661120.388
      1669629.42      661189.832     1669511.364      661232.888
#Sta/Elev= 30
       0  710.31    39.3  707.07      59   705.8    78.7  704.86    88.5  704.67
    98.3  704.83   127.8  706.46   147.5  706.86   157.3  706.76   167.2  706.41
   196.7  704.72   216.3  704.32   226.2  704.51   255.7   705.7   275.3  705.86
   285.2  704.98   293.9  704.94   302.5   704.3   311.2   702.9   319.9  701.49
   328.6  701.36   337.3  703.25     346  706.38     374  712.05   393.3  716.44
   422.3  724.41     432  727.46   441.7  731.11   451.3  735.47   480.3  749.55
#Mann= 3 , 0 , 0
       0     .08       0   311.2    .045       0   337.3      .1       0
Bank Sta=311.2,337.3
XS Rating Curve= 0 ,0
Exp/Cntr=0.3,0.1

Type RM Length L Ch R = 1 ,855     ,63.3,62.3,61.9
XS GIS Cut Line= 6
     1669929.593      661085.701     1669822.171      661107.403
     1669754.897      661108.488     1669672.432      661103.063
     1669650.731      661100.892     1669447.823      661053.149
#Sta/Elev= 30
       0  710.39    18.3  709.81    27.4  709.31    54.8  707.26    63.9  706.75
    82.2  705.98    91.3  705.79   100.5  705.87   109.6   706.2   128.8  707.29
   138.4  707.64   157.6  707.87   167.3  707.63   195.2  706.12   213.6  705.41
   266.8   705.3   290.9  705.61   300.5  705.36     310  704.64   319.6  703.39
   329.2  701.88   338.7   700.7   348.3  701.79   357.8  705.34   367.4  709.24
     377  712.04   405.7  717.97   434.1  724.41   471.2  734.42   489.8  738.89
#Mann= 3 , 0 , 0
       0      .1       0   329.2    .045       0   348.3      .1       0
Bank Sta=329.2,348.3
XS Rating Curve= 0 ,0
Exp/Cntr=0.3,0.1

Type RM Length L Ch R = 1 ,792.7   ,107,107.7,104.7
XS GIS Cut Line= 6
     1669935.019      661026.023     1669827.597      661047.724
     1669760.323      661048.809     1669677.857      661043.384
     1669656.156      661041.214     1669453.248      660993.471
#Sta/Elev= 30
       0  708.73    27.4  708.58    63.9   708.2    73.1  707.91    82.2  707.34
    91.3  706.62   100.5  706.24   138.4  705.83   176.9  704.92   195.2  704.91
   222.8  705.78   241.2  706.15   250.3  706.18   259.5  706.02   300.5  704.54
     310  704.01   319.6  703.28   329.2  702.16   338.7  700.77   348.3  700.01
   357.8  701.04     377  706.15   386.5  707.89   396.1  708.92   415.2  710.45
   443.4   712.9   452.6  713.56   461.9  713.97   480.5  714.46   489.8  714.86
#Mann= 3 , 0 , 0
       0      .1       0   338.7    .045       0   357.8      .1       0
Bank Sta=338.7,357.8
XS Rating Curve= 0 ,0
Exp/Cntr=0.3,0.1

Type RM Length L Ch R = 1 ,685     ,241.8,238.1,234.6
XS GIS Cut Line= 3
     1669840.401       660934.66     1669500.991      660928.366
     1669428.291      660951.153
#Sta/Elev= 19
       0   707.1    19.4  706.72    38.8   706.2      97   704.4   184.3  701.56
     194  701.31   242.5  700.44   252.2  700.12   261.9  699.62   281.6  698.34
     291  698.06   300.7   698.5   310.4  699.61   329.8   702.6   339.5  703.95
   358.5  707.06   377.6  710.01   406.1  713.86   415.7  714.94
#Mann= 3 , 0 , 0
       0      .1       0   281.6    .045       0   300.7      .1       0
Bank Sta=281.6,300.7
XS Rating Curve= 0 ,0
Exp/Cntr=0.3,0.1

Type RM Length L Ch R = 1 ,446.9   ,122.3,123.6,124
XS GIS Cut Line= 2
     1669746.651      660733.271     1669384.889      660732.186
#Sta/Elev= 21
       0  701.95     9.8  701.68    39.1  700.64    78.2   698.7   127.1   697.3
   136.9   697.2   185.8  697.78   195.6  697.76   215.1  697.42   224.9   697.1
   234.7  696.04   242.3  695.04   244.4  694.76   254.2  694.03  257.93695.0283
   283.5  702.06   293.3   704.2   303.1  705.19   312.9  705.71   322.6  706.11
   361.8   707.4
#Mann= 3 , 0 , 0
       0      .1       0   242.3    .045       0  257.93      .1       0
Bank Sta=242.3,257.93
XS Rating Curve= 0 ,0
Exp/Cntr=0.3,0.1

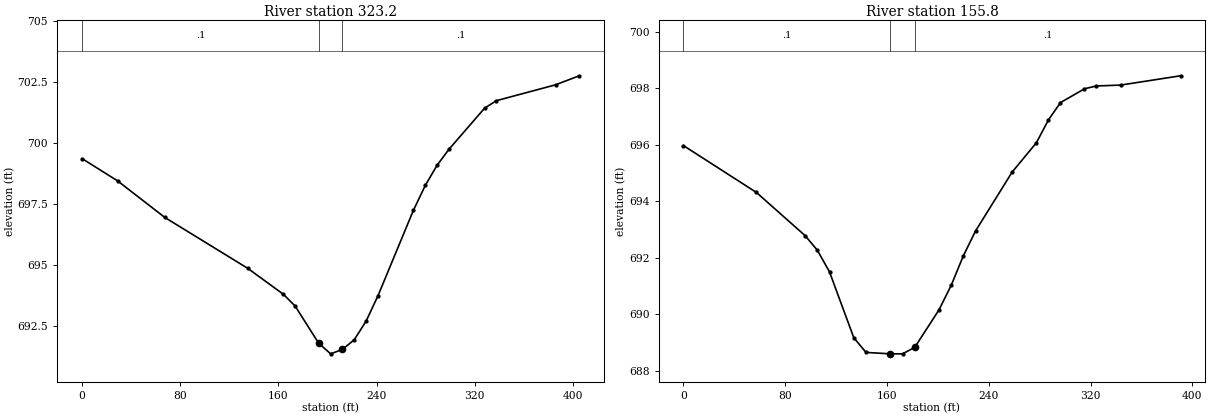
Type RM Length L Ch R = 1 ,323.2   ,167,167.4,178.4
XS GIS Cut Line= 2
     1669740.791      660629.972      1669336.06      660611.526
#Sta/Elev= 20
       0  699.37    28.9  698.46    67.5  696.96     135  694.88     164  693.82
   173.6  693.34   192.9  691.81   202.6  691.38   212.2  691.56   221.9  691.96
   231.5  692.72   241.2  693.76   270.1  697.26   279.8  698.28   289.4   699.1
     299  699.75     328  701.43   337.6  701.74   385.9  702.39   405.2  702.76
#Mann= 3 , 0 , 0
       0      .1       0   192.9    .045       0   212.2      .1       0
Bank Sta=192.9,212.2
XS Rating Curve= 0 ,0
Exp/Cntr=0.3,0.1

Type RM Length L Ch R = 1 ,155.8   ,183,155.9,113.7
XS GIS Cut Line= 3
     1669684.151      660466.344     1669406.807      660458.531
      1669327.38       660539.26
#Sta/Elev= 22
       0  695.97    57.4  694.31    95.7  692.78   105.2  692.27   114.8   691.5
   133.9  689.17   143.5  688.65   162.6   688.6   172.2   688.6   181.8  688.83
   200.9  690.16   210.5  691.03     220  692.07   229.6  692.95   258.3  695.03
   277.4  696.07   286.9  696.88   296.3  697.49   315.2  697.98   324.6  698.08
   343.5  698.11   390.7  698.44
#Mann= 3 , 0 , 0
       0      .1       0   162.6    .045       0   181.8      .1       0
Bank Sta=162.6,181.8
XS Rating Curve= 0 ,0
Exp/Cntr=0.3,0.1

Chan Stop Cuts=-1
Use User Specified Reach Order=0
Composite Channel Slope=5